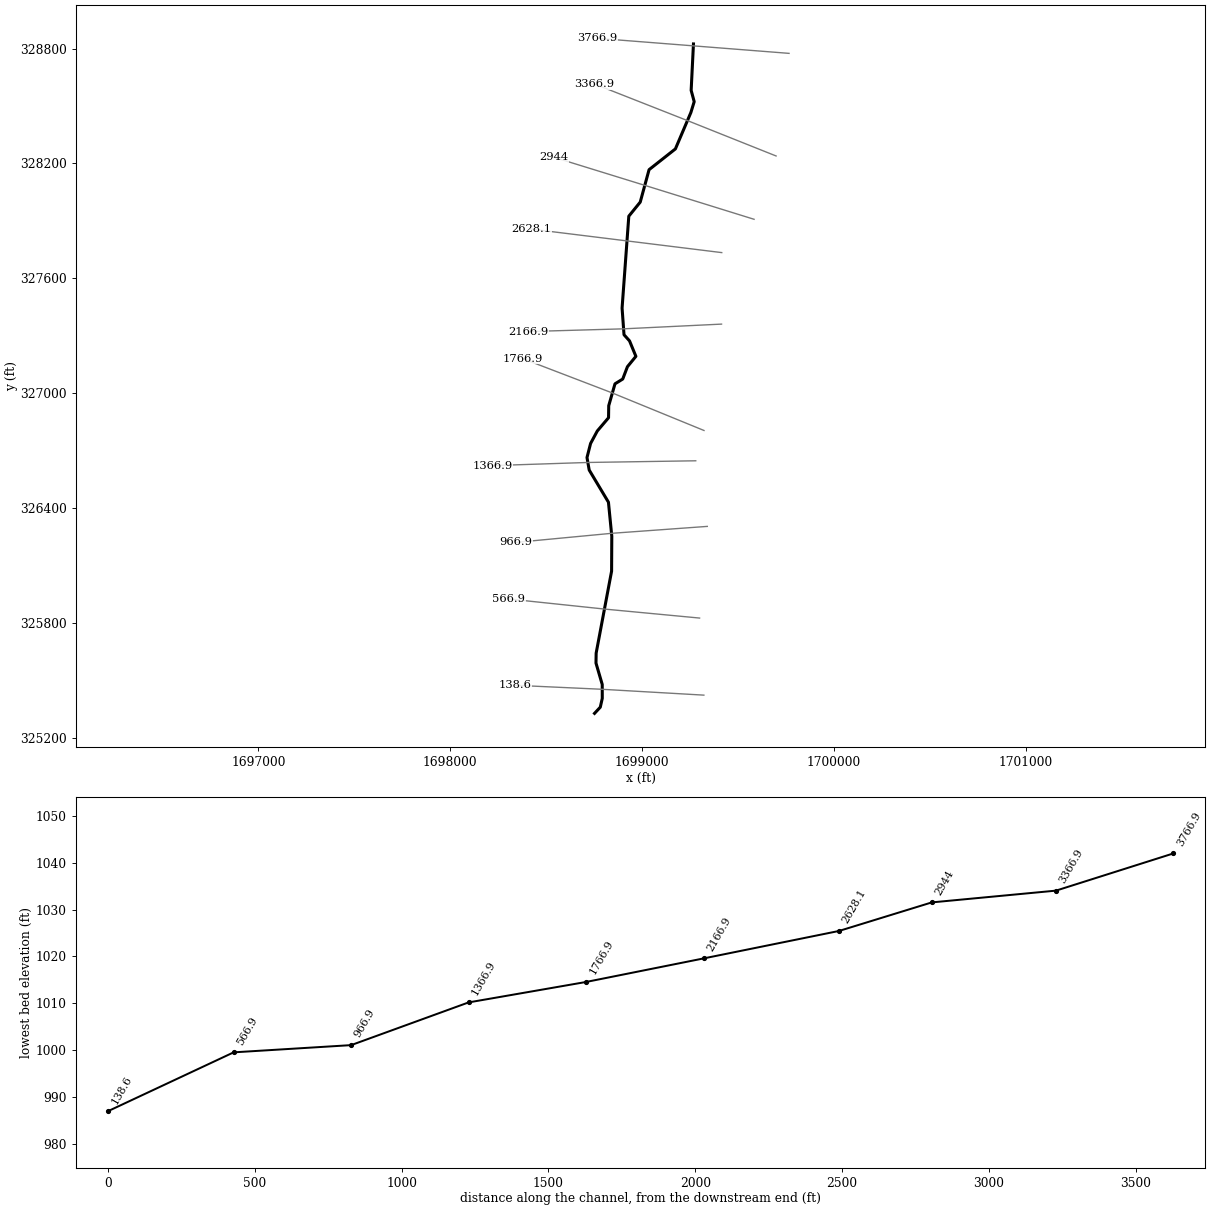
--- LaurlRnE.prj (project) ---

Proj Title=LaurlRnE
Current Plan=p01
Default Exp/Contr=0,0
English Units
Geom File=g01
Flow File=f01
Plan File=p01
BEGIN DESCRIPTION:
END DESCRIPTION:
DSS Export Rating Curves= 0
DSS Export Rating Curve Sorted= 0
DSS Export Volume Flow Curves= 0
DXF OffsetX= 0
DXF OffsetY= 0
DXF ScaleX= 0
DXF ScaleY= 0

--- LaurlRnE.p01 (plan) ---

Plan Title=Floodplain
Program Version=4.00
Geom File=g01
Flow File=f01
K Sum by GR=0
Std Step Tol=0.01
Critical Tol=0.01
Num of Std Step Trials=20
Max Error Tol=0.3
Flow Tol Ratio=0.001
Split Flow NTrial=30
Split Flow Tol=0.02
Split Flow Ratio=0.02
Log Output Level=0
Friction Slope Method=1
Unsteady Friction Slope Method=2
Unsteady Bridges Friction Slope Method=1
Global Log Level=0
CheckData=False
Run HTab=0
Run UNet=0
Run PostProcess=0
UNET Theta=0
UNET Theta Warmup=0
UNET ZTol=0
UNET ZSATol=0
UNET MxIter=0
UNET MaxInSteps=0
UNET DtIC=0
UNET DtMin=0
UNET MaxCRTS=0
UNET WFStab=0
UNET SFStab=0
UNET WFX=0
UNET SFX=0
UNET DSS MLevel=0
UNET DZMax Abort=0
UNET Convert EG Bridges=0
UNET Use Existing IB Tables=0
UNET Froude Limit=0
UNET Froude Power=0
Write IC File=0
Echo Input=False
Echo Output=False
Write Detailed=0

--- LaurlRnE.f01 (steady flow) ---

Flow Title=NFF Regression Equation
Program Version=4.00
Number of Profiles= 1
Profile Names=P100yr
River Rch & RM=LaurlRnE,Main            ,3766.9
788.5428
River Rch & RM=LaurlRnE,Main            ,2944
 808.559
River Rch & RM=LaurlRnE,Main            ,138.6
892.9082
Boundary for River Rch & Prof#=LaurlRnE,Main            , 1
Up Type= 0
Dn Type= 3
Dn Slope=0.0262
DSS Import GetInterval= 0
DSS Import GetPeak= 0
DSS Import FillOption= 0

--- LaurlRnE.g01 (geometry) ---

Geom Title=USGS 3m DEM
Program Version=4.00

River Reach=LaurlRnE     ,Main
Reach XY= 30
     1699267.496      328823.988     1699255.496      328581.589
     1699271.338      328522.549     1699254.055      328465.906
     1699173.416      328275.828     1699036.135      328167.347
     1698990.056      327997.908     1698930.536      327924.469
     1698895.495      327444.466     1698905.578      327305.269
     1698934.377      327273.107     1698967.494      327192.466
     1698923.336      327138.227     1698898.857      327073.907
     1698858.535      327048.947     1698825.896      326934.709
     1698824.936      326871.828     1698766.375      326802.708
     1698731.336      326737.428     1698712.614      326663.986
     1698724.137      326598.706     1698824.456      326430.709
     1698841.885      326252.720     1698840.830      326070.665
     1698760.361      325642.563     1698759.515      325590.395
     1698792.041      325478.882     1698792.251      325406.228
     1698781.901      325360.188     1698751.912      325327.874

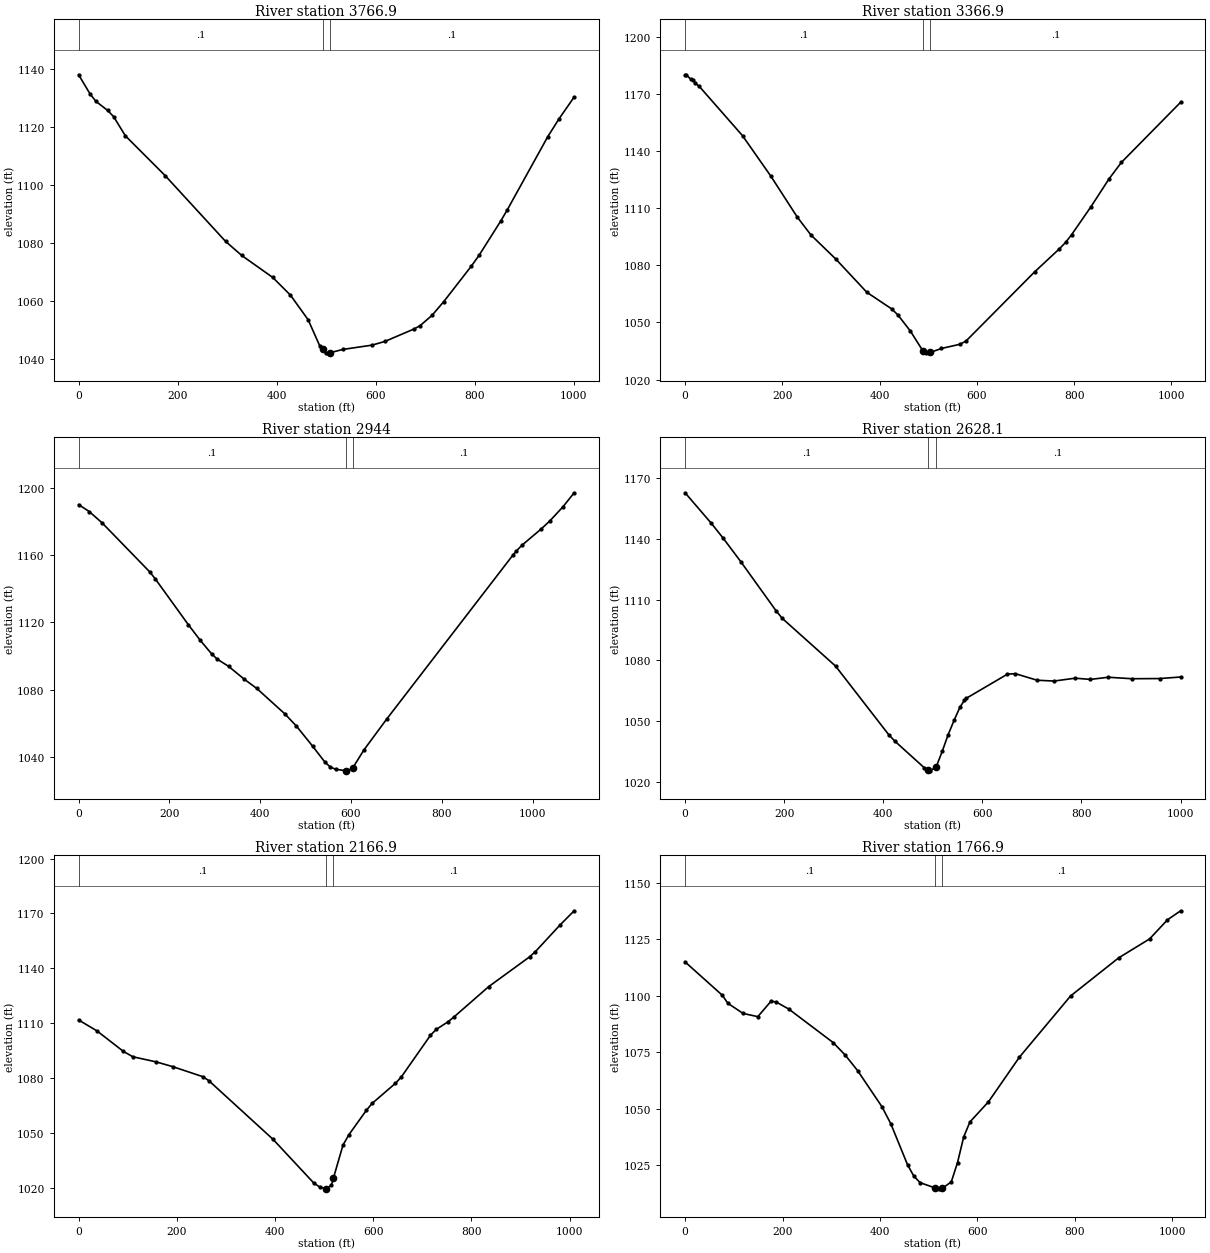
Type RM Length L Ch R = 1 ,3766.9,406.843,400,393.265
XS GIS Cut Line= 3
     1699765.670      328774.769     1699266.711      328814.018
     1698767.753      328853.268
#Sta/Elev= 30
       0 1137.94    22.9 1131.38    34.8 1128.79    58.7 1125.62    70.6 1123.51
    94.4 1116.88   174.9 1103.12   296.8 1080.44   329.5 1075.57   392.1 1067.99
   427.9 1061.88   463.6 1053.39   487.4 1044.26     493 1043.25   499.3 1041.97
     508 1042.04   535.0 1043.18   592.5 1044.62   618.4 1045.89   677.9 1050.23
   689.9 1051.37   713.7 1054.88   737.5 1059.63   793.2 1071.88   808.9 1075.63
   853.3 1087.63   866.2 1091.43   947.7 1116.59   969.8 1122.58  1001.0 1130.27
#Mann= 3 , 0 , 0
       0     0.1       0     493   0.045       0     508     0.1       0
Bank Sta=     493,     508
Exp/Cntr=0.3,0.1

Type RM Length L Ch R = 1 ,3366.9,421.216,422.915,424.533
XS GIS Cut Line= 3
     1699698.111      328238.908     1699237.029      328423.343
     1698750.888      328615.101
#Sta/Elev= 30
       0 1180.25     2.6 1180.20    11.7 1177.84    15.8 1177.71    20.9 1175.79
    28.6 1174.30   118.1 1148.23   176.1 1127.02   230.9 1105.35   258.8 1096.01
   309.9 1083.36   373.8 1065.86   425.0 1057.11   437.8 1053.92   463.4 1045.47
   489.1 1035.05   495.8 1034.11   501.7 1034.03   504.1 1034.24   527.2 1036.32
   565.5 1038.55   577.9 1040.27   718.7 1076.56   769.7 1088.70   782.5 1092.09
   795.2 1096.24   834.5 1110.77   871.8 1125.46   897.4 1134.18  1019.2 1165.80
#Mann= 3 , 0 , 0
       0     0.1       0   489.1   0.045       0   504.1     0.1       0
Bank Sta=   489.1,   504.1
Exp/Cntr=0.3,0.1

Type RM Length L Ch R = 1 ,2944,311.721,315.906,320.063
XS GIS Cut Line= 3
     1699583.385      327908.249     1699017.663      328084.268
     1698540.715      328231.947
#Sta/Elev= 30
       0 1190.27    23.4 1186.13    51.9 1179.33   156.2 1150.28   168.8 1146.01
   241.5 1118.75   268.2 1109.26   293.1 1101.25   305.5 1098.09   330.4 1093.82
   364.8 1086.18   392.6 1080.62   454.7 1065.40   479.6 1058.27   515.4 1046.29
   541.8 1037.00   554.2 1033.84   566.6 1032.43   588.6 1031.62   591.5 1031.52
   603.6 1033.10   628.8 1044.07   678.5 1062.30   956.6 1160.08   964.4 1162.64
   976.8 1166.05  1019.5 1175.83  1038.5 1180.64  1066.9 1188.91  1091.8 1197.32
#Mann= 3 , 0 , 0
       0     0.1       0   588.6   0.045       0   603.6     0.1       0
Bank Sta=   588.6,   603.6
Exp/Cntr=0.3,0.1

Type RM Length L Ch R = 1 ,2628.1,457.31,461.179,464.602
XS GIS Cut Line= 3
     1699414.932      327734.255     1698918.213      327795.659
     1698421.494      327857.063
#Sta/Elev= 30
       0 1162.69    52.3 1147.80    76.4 1140.42   112.3 1128.72   184.0 1104.30
   196.0 1100.72   303.7 1077.13   411.3 1043.16   423.3 1040.09   483.1 1026.86
   490.6 1025.98   495.1 1025.43   505.6 1027.26   507.0 1027.54   519.0 1035.10
   531.0 1043.33   542.9 1050.37   554.9 1056.95   563.6 1060.17   566.9 1061.16
   650.6 1073.17   666.6 1073.39   710.4 1070.16   744.6 1069.75   787.2 1071.17
   818.1 1070.56   854.0 1071.63   901.8 1070.90   957.5 1070.98  1000.1 1071.75
#Mann= 3 , 0 , 0
       0     0.1       0   490.6   0.045       0   505.6     0.1       0
Bank Sta=   490.6,   505.6
Exp/Cntr=0.3,0.1

Type RM Length L Ch R = 1 ,2166.9,409.595,400,391.358
XS GIS Cut Line= 3
     1699413.902      327360.820     1698903.172      327336.116
     1698405.469      327321.908
#Sta/Elev= 30
       0 1111.81    37.3 1105.87    91.2 1094.65   110.5 1091.72   158.1 1088.91
   191.2 1086.37   252.7 1080.87   265.0 1078.71   395.8 1046.65   479.0 1022.72
   490.8 1020.61   502.8 1019.57   503.8 1019.72   514.7 1021.43   518.8 1025.35
   538.4 1043.49   550.3 1049.09   585.9 1062.44   597.8 1066.26   645.3 1077.24
   657.2 1080.71   716.6 1103.48   728.4 1106.70   752.2 1110.80   764.1 1113.41
   835.3 1130.08   918.5 1146.32   930.4 1149.21   980.4 1163.72  1009.2 1171.48
#Mann= 3 , 0 , 0
       0     0.1       0   503.8   0.045       0   518.8     0.1       0
Bank Sta=   503.8,   518.8
Exp/Cntr=0.3,0.1

Type RM Length L Ch R = 1 ,1766.9,390.895,400,408.996
XS GIS Cut Line= 3
     1699322.440      326805.277     1698840.795      327002.733
     1698376.840      327180.825
#Sta/Elev= 30
       0 1114.89    76.4 1100.15    87.6 1096.63   118.9 1092.12   149.2 1090.69
   176.5 1097.56   187.3 1097.12   212.8 1094.04   303.9 1079.22   328.4 1073.74
   354.1 1066.81   404.0 1050.85   422.2 1043.30   456.7 1025.08   469.6 1020.11
   482.4 1017.27     513 1014.95   520.5 1014.55     528 1014.80   546.3 1017.64
   559.0 1026.12   571.7 1037.49   584.5 1044.13   622.6 1053.06   686.2 1072.82
   791.1 1099.85   889.7 1116.69   953.3 1125.08   989.9 1133.52  1016.9 1137.51
#Mann= 3 , 0 , 0
       0     0.1       0     513   0.045       0     528     0.1       0
Bank Sta=     513,     528
Exp/Cntr=0.3,0.1

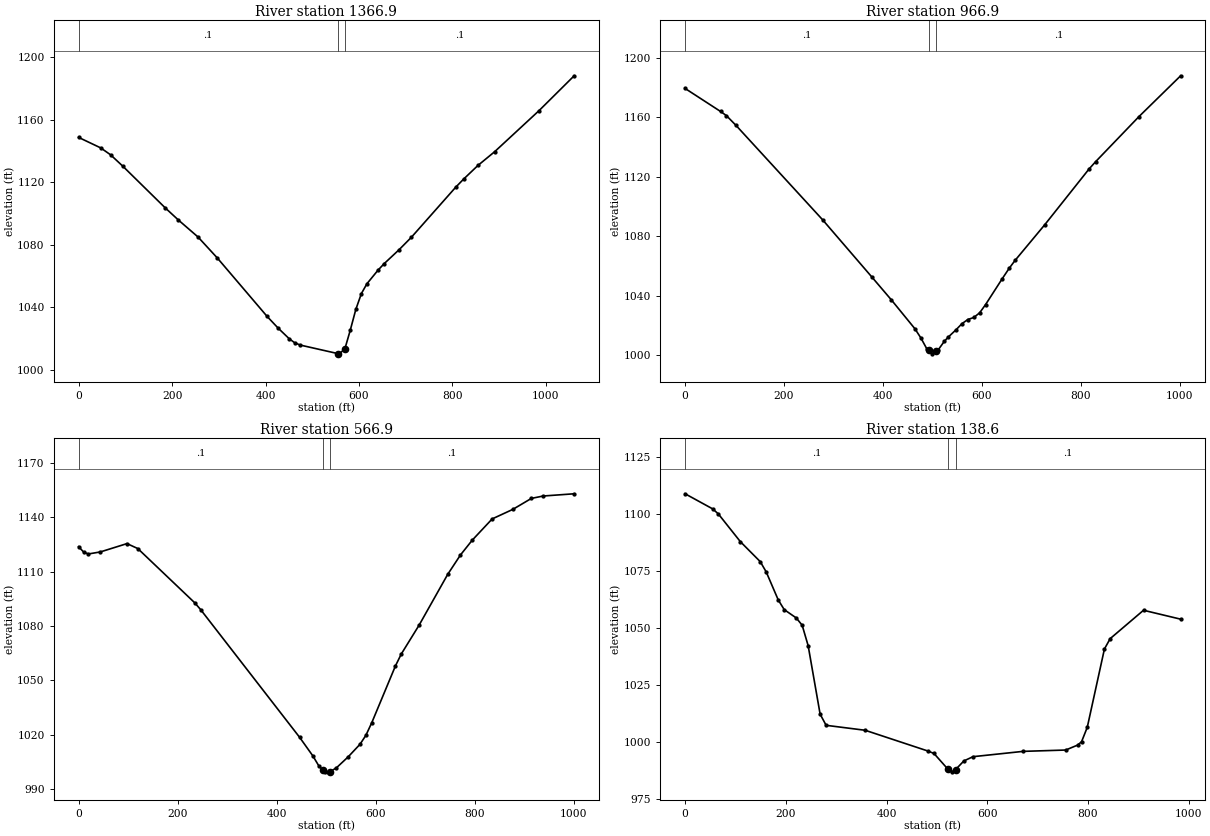
Type RM Length L Ch R = 1 ,1366.9,398.699,400,401.406
XS GIS Cut Line= 3
     1699279.439      326647.015     1698717.157      326638.250
     1698219.048      326621.874
#Sta/Elev= 30
       0 1148.80    47.2 1142.09    68.3 1137.68    94.7 1130.33   185.2 1103.72
   213.4 1095.93   255.4 1085.06   296.5 1071.70   403.4 1034.17   427.1 1026.64
   450.9 1019.82   462.8 1017.21   474.6 1015.79   554.8 1010.35   557.7 1010.19
   569.8 1013.27   581.5 1025.39   593.4 1038.72   605.3 1048.83   617.1 1055.07
   640.9 1063.80   654.2 1068.01   685.9 1076.87   712.2 1084.82   807.2 1116.92
   823.9 1122.05   854.7 1130.84   890.4 1139.62   985.4 1165.92  1060.7 1188.27
#Mann= 3 , 0 , 0
       0     0.1       0   554.8   0.045       0   569.8     0.1       0
Bank Sta=   554.8,   569.8
Exp/Cntr=0.3,0.1

Type RM Length L Ch R = 1 ,966.9,403.788,400,395.471
XS GIS Cut Line= 3
     1699339.553      326304.373     1698840.579      326268.172
     1698340.882      326220.682
#Sta/Elev= 30
       0 1179.45    71.8 1163.97    83.7 1161.15   103.0 1154.61   278.0 1091.22
   377.9 1052.64   417.1 1037.37   464.7 1017.97   476.6 1011.90   488.5 1004.66
   492.8 1003.37   500.3 1001.08   507.8 1002.79   512.3 1003.96   524.2 1009.46
   532.6 1012.47   548.1 1017.29   560.0 1021.38   571.9 1024.16   583.9 1025.51
   595.8 1028.69   607.7 1034.20   641.5 1051.63   655.4 1058.55   667.3 1063.86
   727.0 1087.69   817.2 1125.42   830.3 1130.25   917.8 1160.50  1002.2 1187.97
#Mann= 3 , 0 , 0
       0     0.1       0   492.8   0.045       0   507.8     0.1       0
Bank Sta=   492.8,   507.8
Exp/Cntr=0.3,0.1

Type RM Length L Ch R = 1 ,566.9,427.424,428.246,429.51
XS GIS Cut Line= 3
     1699299.497      325825.641     1698801.239      325872.902
     1698303.437      325925.453
#Sta/Elev= 30
       0 1123.80    10.6 1120.70    19.8 1119.80    43.7 1120.90    97.7 1125.51
   119.5 1122.78   234.5 1092.85   246.4 1089.11   446.3 1018.64   473.0 1008.41
   484.9 1002.99     493 1000.62   496.8  999.54     508  999.67   520.7 1001.73
   544.6 1007.83   568.5 1014.77   580.4 1019.73   592.4 1026.77   640.1 1058.05
   651.9 1064.61   687.9 1080.53   745.6 1108.53   771.4 1119.24   795.3 1127.44
   835.5 1139.15   877.1 1144.39   914.7 1150.46   938.6 1151.78  1001.1 1153.01
#Mann= 3 , 0 , 0
       0     0.1       0     493   0.045       0     508     0.1       0
Bank Sta=     493,     508
Exp/Cntr=0.3,0.1

Type RM Length L Ch R = 1 ,138.6,154.467,138.639,122.608
XS GIS Cut Line= 3
     1699321.870      325423.128     1698787.988      325453.870
     1698339.380      325474.475
#Sta/Elev= 30
       0 1108.79    54.7 1102.18    65.9 1099.99   109.7 1087.82   149.2 1079.06
   161.1 1074.53   184.9 1062.30   196.8 1058.04   220.6 1054.41   232.4 1051.22
   244.3 1042.25   268.1 1012.22   280.0 1007.36   357.5 1005.19   482.2  996.09
   494.1  995.03   522.1  988.06   529.8  986.98   537.1  988.00   553.5  991.77
   571.6  993.62   671.2  995.95   755.6  996.53   779.3  998.70   787.1 1000.17
   798.4 1006.46   832.5 1040.80   843.9 1045.33   910.1 1057.76   983.8 1053.86
#Mann= 3 , 0 , 0
       0     0.1       0   522.1   0.045       0   537.1     0.1       0
Bank Sta=   522.1,   537.1
Exp/Cntr=0.3,0.1